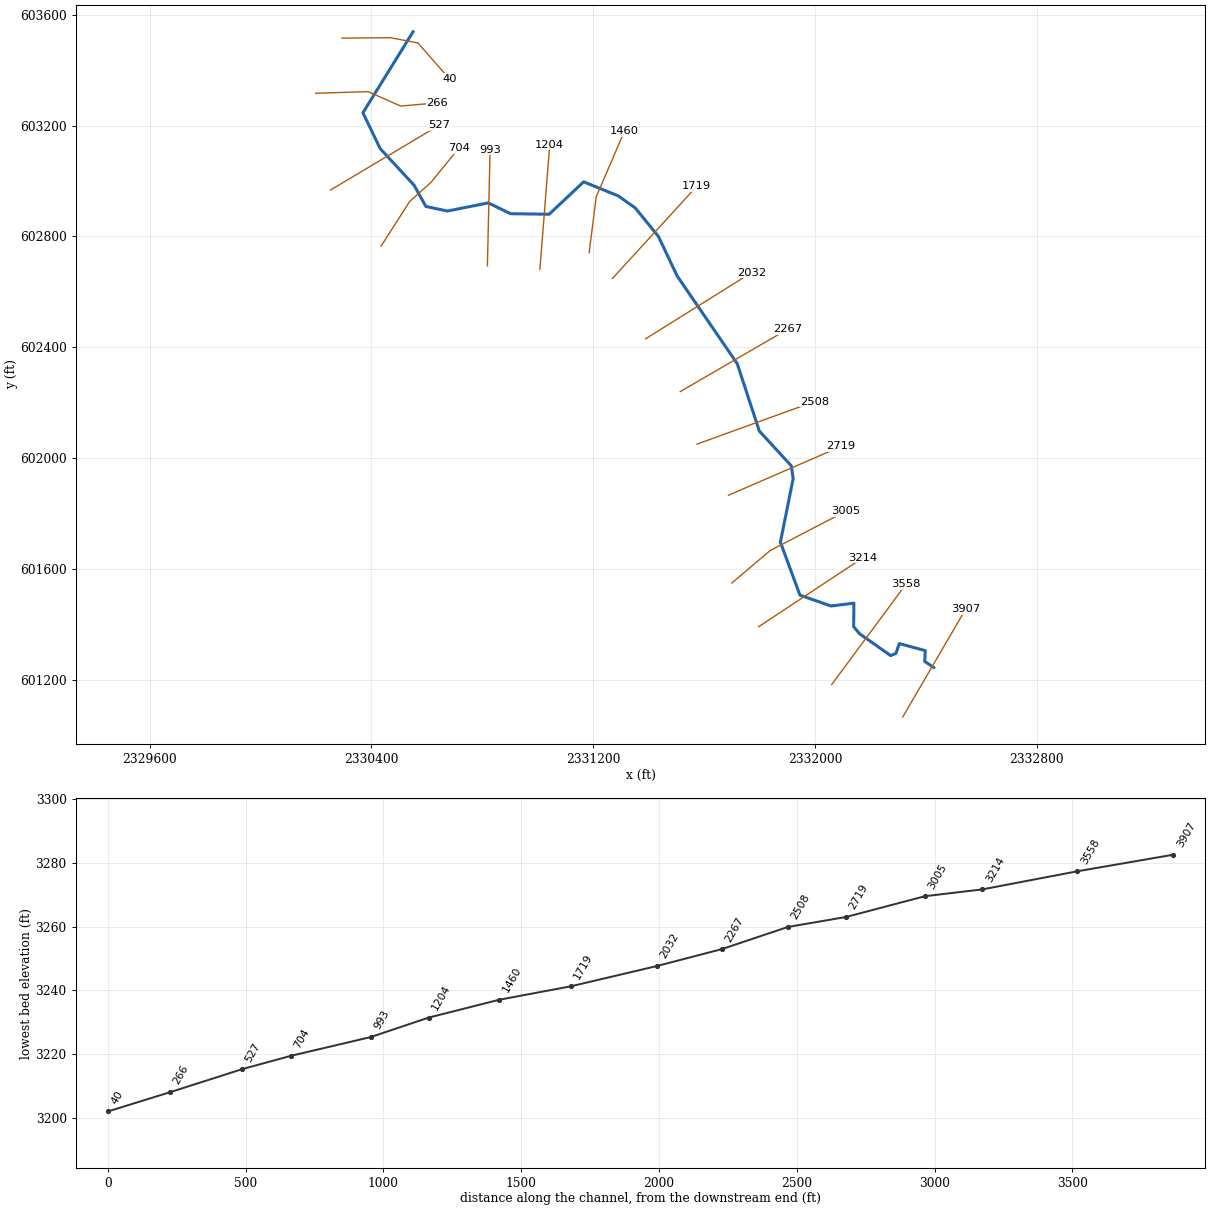
--- HNKLERN.prj (project) ---

Proj Title=HNKLERN
Current Plan=p01
Default Exp/Contr=0,0
English Units
Geom File=g01
Flow File=f01
Plan File=p01
Background Map Layer=Inundation Boundary (01pct Value_0)
BEGIN DESCRIPTION:
----------MODEL BY WOOD PLC 2021----------
Stream Name: Hinkle Run
Flood Zone: Enhanced Approximate
Pocahontas County, WV
HEC-RAS Version: RAS 6.1
Vertical Datum: NAVD88
Projection: NAD 1983 StatePlane West Virginia S FIPS 4702 (US Feet)
Terrain: 1-meter LIDAR (FEMA Region III 3DEP collected 2016-2018)
Land Use: 2019 NLCD
Hydrologic Method:
WV SIR2010-5033 regression equations
Model Notes:
Normal depth tie in to Little River II
END DESCRIPTION:
DSS Export Rating Curves= 0
DSS Export Rating Curve Sorted= 0
DSS Export Volume Flow Curves= 0
DXF OffsetX= 0
DXF OffsetY= 0
DXF ScaleX= 0
DXF ScaleY= 0

--- HNKLERN.p01 (plan) ---

Plan Title=Floodplain
Program Version=6.10
Short Identifier=Floodplain
Geom File=g01
Flow File=f01
Subcritical Flow
K Sum by GR= 0
Std Step Tol= 0.01
Critical Tol= 0.01
Num of Std Step Trials= 20
Max Error Tol= 0.3
Flow Tol Ratio= 0.001
Split Flow NTrial= 30
Split Flow Tol= 0.02
Split Flow Ratio= 0.02
Log Output Level= 0
Friction Slope Method= 1
Unsteady Friction Slope Method= 2
Unsteady Bridges Friction Slope Method= 1
Parabolic Critical Depth
Global Vel Dist= 0 , 0 , 0
Global Log Level= 0
CheckData=False
Encroach Param=-1 ,0,0, 0
Mapping Interval=1HOUR
Computation Time Step Use Courant=        0
Computation Time Step Use Time Series=    0
Computation Time Step Count To Double=0
Computation Time Step Max Doubling=0
Computation Time Step Max Halving=0
Computation Time Step Residence Courant=0
Run HTab= 0
Run UNet= 0
Run Sediment= 0
Run PostProcess= 0
Run WQNet= 0
Run RASMapper=-1
UNET Theta= 0
UNET Theta Warmup= 0
UNET ZTol= 0
UNET ZSATol= 0
UNET MxIter= 0
UNET Max Iter WO Improvement= 0
UNET MaxInSteps= 0
UNET DtIC= 0
UNET DtMin= 0
UNET MaxCRTS= 0
UNET WFStab= 0
UNET SFStab= 0
UNET WFX= 1
UNET SFX= 1
UNET Gravity=32.174
UNET 1D Methodology=Finite Difference
UNET DSS MLevel= 1
UNET Pardiso=0
UNET DZMax Abort= 0
UNET Use Existing IB Tables= 0
UNET Froude Reduction=False
UNET Froude Limit= 0
UNET Froude Power= 0
UNET D1 Cores= 0
UNET WindReference=Eulerian
UNET WindDragFormulation=Hsu (1988)
UNET D2 Coriolis=0
UNET D2 Cores= 0
UNET D2 Theta= 1
UNET D2 Theta Warmup= 1
UNET D2 Z Tol= 0.01
UNET D2 Volume Tol= 0.01
UNET D2 Max Iterations= 20
UNET D2 Equation= 0
UNET D2 RampUpFraction=0.1
UNET D2 TimeSlices= 1
UNET D2 Turbulence Formulation=Non-Conservative (original)
UNET D2 Eddy Viscosity=0.3
UNET D2 Transverse Eddy Viscosity=0.1
UNET D2 Smagorinsky Mixing=0
UNET D2 BCVolumeCheck=0
UNET D2 Cores=0
UNET D2 SolverType=PARDISO (Direct)
UNET D2 Minimum Iterations= 2147483647
UNET D2 Maximum Iterations= 2147483647
UNET D2 Restart Number= 10
UNET D2 Relaxation Coeff=1.3
UNET D2 SOR Precondition Iterations= 10
UNET D2 ILUT Maximum Fill= 8
UNET D2 ILUT Tolerance=1E-08
UNET D1D2 MaxIter= 0
UNET D1D2 ZTol=0.01
UNET D1D2 QTol=0.1
UNET D1D2 MinQTol=1
Write IC File= 0
Write IC File at Fixed DateTime=0
Write IC File at Sim End=0
Echo Input=False
Echo Parameters=False
Echo Output=False
Write Detailed= 0
HDF Write Warmup=0
HDF Write Time Slices=0
HDF Flush=0
HDF Compression= 1
HDF Chunk Size= 1
HDF Spatial Parts= 1
HDF Use Max Rows=0
HDF Fixed Rows= 1
Calibration Method= 0
Calibration Iterations= 20
Calibration Max Change=0.05
Calibration Tolerance=0.2
Calibration Maximum=1.5
Calibration Minimum=0.5
Calibration Optimization Method= 1
WQ AD Non Conservative
WQ ULTIMATE=-1
WQ Max Comp Step=1HOUR
WQ Output Interval=15MIN
WQ Output Selected Increments= 0
WQ Output face flow=0
WQ Output face velocity=0
WQ Output face area=0
WQ Output face dispersion=0
WQ Output cell volume=0
WQ Output cell surface area=0
WQ Output cell continuity=0
WQ Output cumulative cell continuity=0
WQ Output face conc=0
WQ Output face dconc_dx=0
WQ Output face courant=0
WQ Output face peclet=0
WQ Output face adv mass=0
WQ Output face disp mass=0
WQ Output cell mass=0
WQ Output cell source sink temp=0
WQ Output nsm pathways=0
WQ Output nsm derived pathways=0
WQ Create Restart=0
WQ Fixed Restart=0
WQ System Summary=0
WQ Write To DSS=0
Sorting and Armoring Iterations= 10
XS Update Threshold= 0.02
Bed Roughness Predictor= 0
Hydraulics Update Threshold= 0.02
Energy Slope Method= 1
Volume Change Method= 1
Sediment Retention Method= 0
Sediment TS Multiplier= 1
Warm Up Method= 0
XS Weighting Method= 0
Number of US Weighted Cross Sections= 1
Number of DS Weighted Cross Sections= 1
Upstream XS Weight=0
Main XS Weight=1
Downstream XS Weight=0
Number of DS XS's Weighted with US Boundary= 1
Upstream Boundary Weight= 1
Weight of XSs Associated with US Boundary= 0
Number of US XS's Weighted with DS Boundary= 1
Downstream Boundary Weight= 0.5
Weight of XSs Associated with DS Boundary= 0.5
Percentile Method= 0
Sediment Output Level= 3
Mass or Volume Output= 0
Output Increment Type= 1
Profile and TS Output Increment= 1
Transport Output Increment 1
XS Output Flag= 0
XS Output Increment= 10
Read HDF5 Sediment Hotstart= 0
Sediment Hotstart Type= 0
Write Gradation File= 0
Read Gradation Hotstart= 0
Write HDF5 File= 1
Write Binary Output= 1
Write DSS Sediment File= 0
DSS Sediment Output Type= 1
SV Curve= 0
Specific Gage Flag= 0
Subcell Erosion Methods= 0
Subcell Deposition Methods= 0
Advection Scheme= 1
Matrix Solver= 0
Implicit Weighting Factor= 1
Maximum Outer Loop Convergence Iterations= 5
Convergence Maximum Absolute= 0.001
Convergence RMSE= 0.0001
Grain Fractions Max Abs Error= 0.001
Max Subgrid Regions= 1
Max Subgrid Length Scale= 3.402823E+38
Initial Layer Thickness= 3.402823E+38
Min Layer Thickness= 3.402823E+38
Max Layer Thickness= 3.402823E+38
Number of Layers= 5

--- HNKLERN.f01 (steady flow) ---

Flow Title=Flow
Program Version=6.10
Number of Profiles= 6
Profile Names=01pct,10pct,04pct,02pct,0_2pct,01plus
River Rch & RM=HNKLRN,Main            ,3907
     727     388     513     617    1010    1080
River Rch & RM=HNKLERN,Main            ,3907
     727     388     513     617    1010    1080
Boundary for River Rch & Prof#=HNKLERN,Main            , 1
Up Type= 0
Dn Type= 3
Dn Slope=0.02636
Boundary for River Rch & Prof#=HNKLERN,Main            , 2
Up Type= 0
Dn Type= 3
Dn Slope=0.02636
Boundary for River Rch & Prof#=HNKLERN,Main            , 3
Up Type= 0
Dn Type= 3
Dn Slope=0.02636
Boundary for River Rch & Prof#=HNKLERN,Main            , 4
Up Type= 0
Dn Type= 3
Dn Slope=0.02636
Boundary for River Rch & Prof#=HNKLERN,Main            , 5
Up Type= 0
Dn Type= 3
Dn Slope=0.02636
Boundary for River Rch & Prof#=HNKLERN,Main            , 6
Up Type= 0
Dn Type= 3
Dn Slope=0.02636
DSS Import GetInterval= 0
DSS Import GetPeak= 0
DSS Import FillOption= 0

--- HNKLERN.g01 (geometry) ---

Geom Title=Geometry
Program Version=6.10

River Reach=HNKLERN         ,Main
Reach XY= 30
     2332428.515      601245.451     2332395.761      601267.488
     2332397.913      601306.336     2332304.364      601331.628
     2332291.894      601296.288     2332272.815      601288.509
     2332160.478      601367.6542332139.54727338601392.642479175
     2332140.358      601477.4872332057.82937973601467.325057486
2331945.80551226601506.289880953     2331875.272      601697.611
     2331921.309      601926.806     2331914.733      601972.722
2331799.25221896602098.366618008     2331719.526       602341.44
2331503.05123038602657.413345725     2331435.073       602800.66
     2331351.606      602903.123     2331290.852      602946.277
     2331165.666      602997.177     2331041.228      602880.275
     2330902.091      602882.226     2330821.665      602921.134
     2330674.373      602891.805     2330596.675       602908.25
     2330554.108      602984.831     2330431.628      603117.308
     2330369.526       603246.24     2330550.478      603538.447

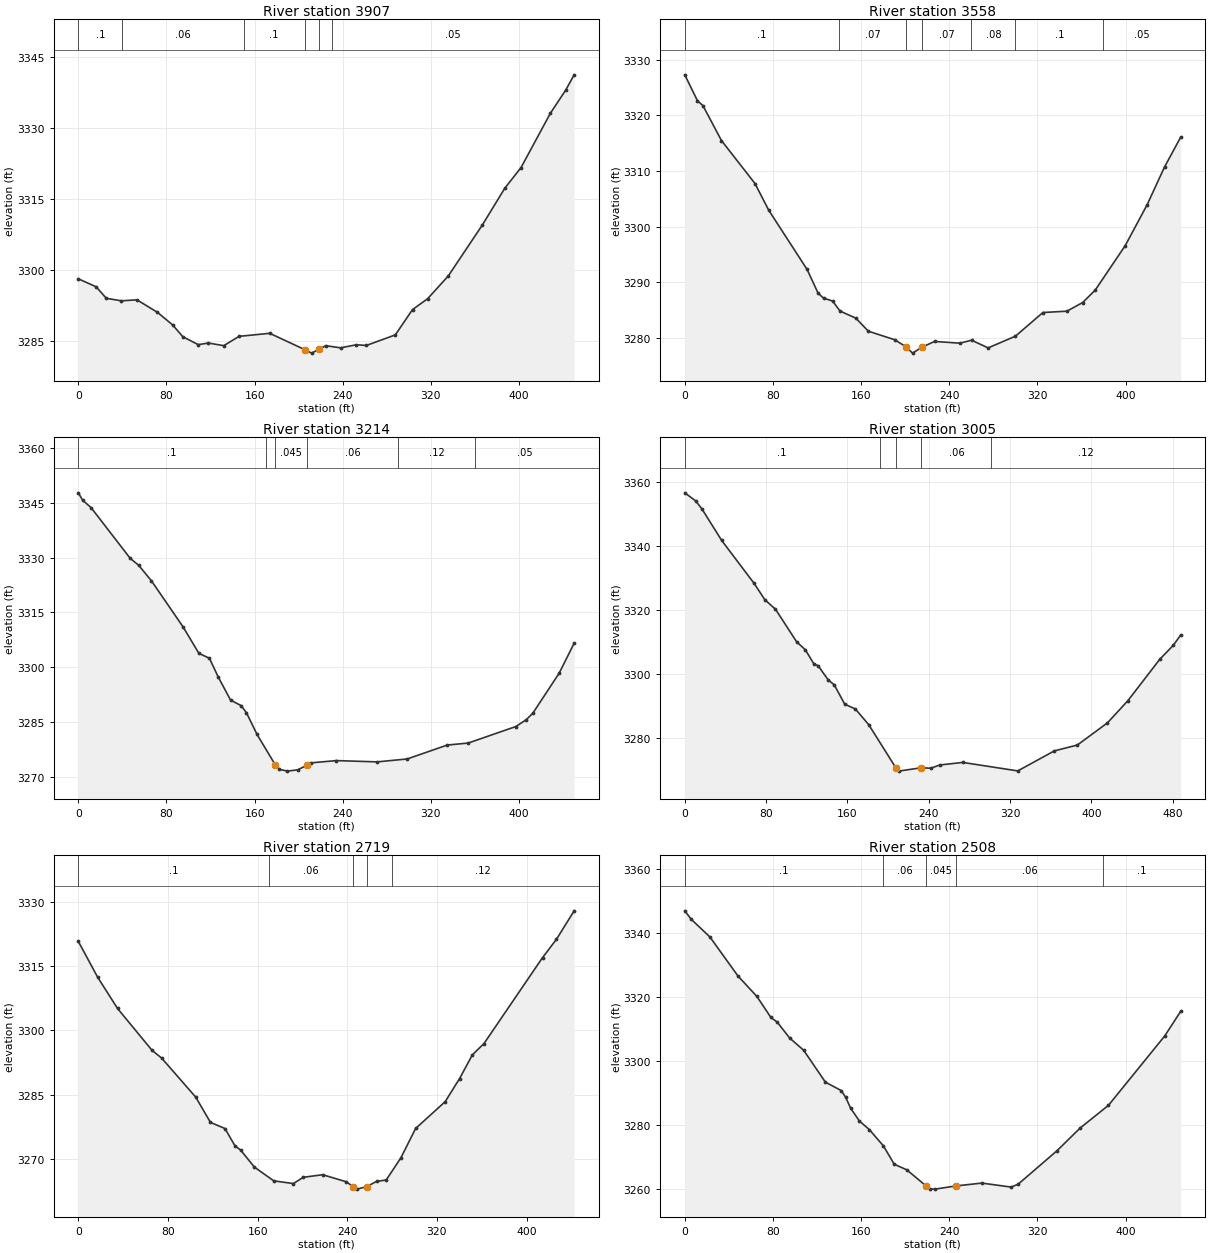
Type RM Length L Ch R = 1 ,3907    ,348.8,348.8,348.8
XS GIS Cut Line= 2
2332316.63480841601067.2082315072332543.47966163601455.848698475
#Sta/Elev= 30
       0 3298.18    16.2 3296.49    25.4 3294.06    39.1 3293.53    53.2 3293.74
    71.8  3291.1    85.6 3288.43    94.9 3285.92   108.8 3284.27   118.1  3284.6
     132 3284.05   145.9 3286.02   173.7 3286.66   205.4 3283.22   211.7 3282.47
   218.1 3283.24   224.6 3284.04     238 3283.59   252.4 3284.24   261.4 3284.09
   287.7 3286.33   303.3 3291.68     317 3293.97   335.8  3298.8   366.7 3309.57
   387.1 3317.35   401.8 3321.71   428.4 3333.18   442.3 3338.07     450 3341.31
#Mann= 6 ,-1,0
       0      .1       0      40     .06       0     150      .1       0
   205.4    .045       0   218.1      .1       0     230     .05       0
Bank Sta=205.4,218.1
XS Rating Curve= 0 ,0
Exp/Cntr(USF)=0,0
Exp/Cntr=0.3,0.1

Type RM Length L Ch R = 1 ,3558    ,348.6,344.3,331.9
XS GIS Cut Line= 2
2332060.34271618601183.9543084592332328.08869459601545.633850381
#Sta/Elev= 30
       0 3327.31    11.5 3322.65    16.5 3321.76    33.3 3315.49    63.7 3307.77
    76.2 3302.96     111 3292.32     121 3288.05   125.9 3287.17   134.2 3286.64
   140.9 3284.84   155.2 3283.57   166.6 3281.22   190.6 3279.68   200.6 3278.44
   206.7 3277.28   215.5 3278.37   226.7 3279.38   249.6 3279.07   260.3  3279.6
   275.3 3278.22   300.1 3280.33     325 3284.58   346.8 3284.82   361.1 3286.38
   372.5 3288.61   399.7  3296.6   419.6 3303.95   435.4 3310.75     450 3316.08
#Mann= 7 ,-1,0
       0      .1       0     140     .07       0   200.6    .045       0
   215.5     .07       0     260     .08       0     300      .1       0
     380     .05       0
Bank Sta=200.6,215.5
XS Rating Curve= 0 ,0
Exp/Cntr(USF)=0,0
Exp/Cntr=0.3,0.1

Type RM Length L Ch R = 1 ,3214    ,209.5,209,206.6
XS GIS Cut Line= 2
2331796.87341177601392.5965187022332172.31638675601640.674273723
#Sta/Elev= 30
       0 3347.72       4 3345.66    11.5  3343.7    47.1  3329.8    54.8  3327.9
    66.4 3323.64    95.2    3311   109.4 3303.83     119 3302.48   126.9  3297.4
   138.2 3291.03   147.8 3289.53   152.6 3287.58   162.2 3281.65   178.9 3273.26
   182.5 3272.12   189.7 3271.62   199.1 3271.97   207.8 3273.28   211.5 3273.89
   234.1  3274.5   271.3 3274.15   298.5 3274.95   334.8 3278.75   353.9  3279.3
   397.1 3283.82   406.7 3285.72   412.7 3287.55   436.4 3298.41     450 3306.61
#Mann= 6 ,-1,0
       0      .1       0     170     .06       0   178.9    .045       0
   207.8     .06       0     290     .12       0     360     .05       0
Bank Sta=178.9,207.8
XS Rating Curve= 0 ,0
Exp/Cntr(USF)=0,0
Exp/Cntr=0.3,0.1

Type RM Length L Ch R = 1 ,3005    ,286.7,285.9,279.4
XS GIS Cut Line= 3
2331700.11424208 601550.205838972331838.63710986601667.523619418
2332110.33886726601808.616194872
#Sta/Elev= 30
       0 3356.76    10.8  3354.2      17 3351.64    36.2 3341.86    68.2 3328.35
    78.7 3323.25    89.2 3320.26     110 3310.04   118.5 3307.55     127 3303.09
   131.1 3302.56   141.2 3298.02     147 3296.56   157.3 3290.48   167.8 3288.96
     181 3284.01   207.6 3270.52   210.3 3269.48   232.8 3270.55   241.9 3270.38
   250.9 3271.41   273.4 3272.21   327.5 3269.55   363.5 3275.83   386.1 3277.66
   415.7 3284.61   435.7 3291.53   467.2 3304.56   480.6 3308.97   487.7 3312.15
#Mann= 5 ,-1,0
       0      .1       0  191.53     .06       0   207.6    .045       0
   232.8     .06       0  301.53     .12       0
Bank Sta=207.6,232.8
XS Rating Curve= 0 ,0
Exp/Cntr(USF)=0,0
Exp/Cntr=0.3,0.1

Type RM Length L Ch R = 1 ,2719    ,211,210.9,205.5
XS GIS Cut Line= 2
2331688.03412942601866.751489504 2332093.9884501602042.775344179
#Sta/Elev= 30
       0 3320.78    17.2 3312.45      35 3305.13    65.8 3295.36    74.3 3293.57
   104.8 3284.44   117.9 3278.56   130.9 3277.11   139.7 3273.12   144.9 3272.08
   157.1 3268.12   174.5  3264.9     192 3264.28   200.7 3265.74   218.1 3266.34
   239.2 3264.69   245.2 3263.56   248.7 3262.98   257.4 3263.57   266.1 3264.77
   274.8 3265.12   287.9  3270.3     301 3277.13   327.4 3283.39   340.2 3288.76
   351.7 3294.33     362 3296.94   414.3 3317.01   426.7 3321.28   442.5 3327.92
#Mann= 5 ,-1,0
       0      .1       0     170     .06       0   245.2    .045       0
   257.4     .06       0     280     .12       0
Bank Sta=245.2,257.4
XS Rating Curve= 0 ,0
Exp/Cntr(USF)=0,0
Exp/Cntr=0.3,0.1

Type RM Length L Ch R = 1 ,2508    ,238.3,240.4,242.9
XS GIS Cut Line= 2
2331574.70772081602051.1907430092331997.76622256602204.557962763
#Sta/Elev= 30
       0 3346.94     5.8 3344.31    22.8 3338.76    48.4 3326.49    65.4 3320.17
    78.1  3313.6    83.9 3312.11    95.2 3307.14   107.9 3303.31   127.6 3293.34
     142  3290.7     146 3288.61   150.5  3285.2   158.4  3281.2   167.5 3278.49
   180.3 3273.38   190.1 3267.66   201.5  3265.9   218.6 3260.98   222.8 3259.94
   227.1 3259.87   246.3 3260.88   269.6 3261.76   296.2 3260.51   302.5  3261.4
   337.7 3271.85   358.7 3278.95   384.5 3286.09   435.5 3307.76     450 3315.46
#Mann= 5 ,-1,0
       0      .1       0     180     .06       0   218.6    .045       0
   246.3     .06       0     380      .1       0
Bank Sta=218.6,246.3
XS Rating Curve= 0 ,0
Exp/Cntr(USF)=0,0
Exp/Cntr=0.3,0.1

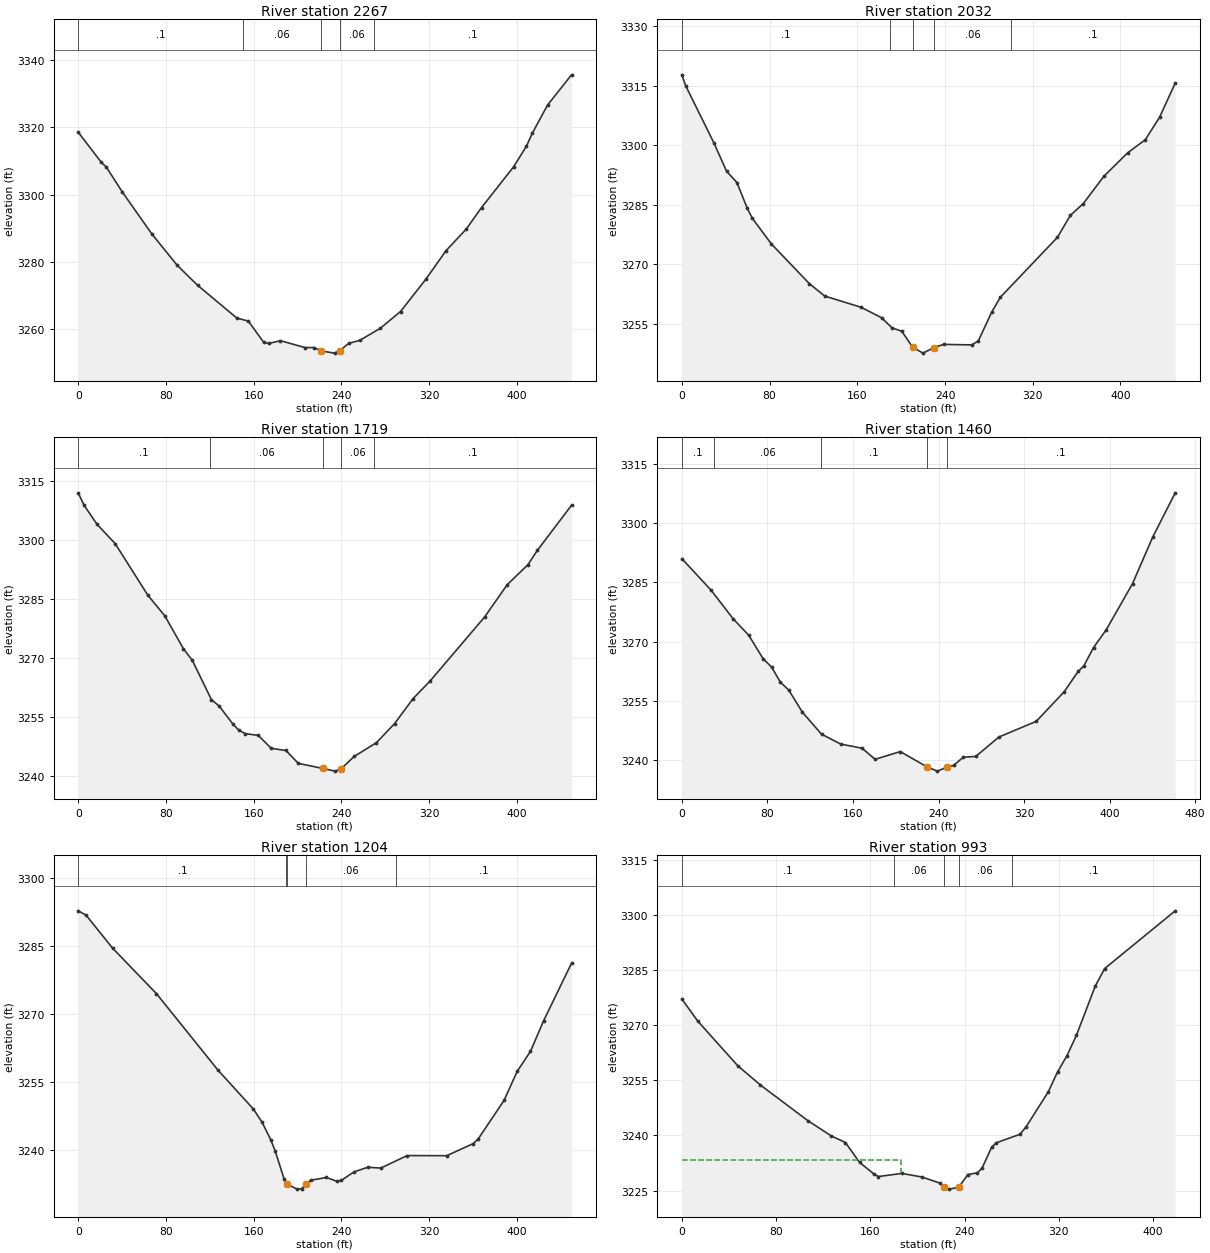
Type RM Length L Ch R = 1 ,2267    ,235.6,235.6,236.3
XS GIS Cut Line= 2
2331513.96430851602240.5067607572331903.11253418602466.479454808
#Sta/Elev= 30
       0 3318.53    21.1 3309.57    25.7 3308.15    40.2 3300.78    67.3 3288.25
    90.4 3278.96   108.9 3273.07   144.7 3263.33   155.2 3262.43   169.1 3256.18
   173.7 3255.78   184.5 3256.61   206.9 3254.57   215.3 3254.57   221.6 3253.57
   233.8 3252.92   238.5 3253.64   246.9 3255.85   256.7 3256.68   275.5 3260.28
     294 3265.27   317.1 3274.85   335.6 3283.37   354.1  3289.8   367.9 3296.14
   397.2 3308.25   408.9 3314.38   414.2  3318.2   428.1 3326.56     450 3335.56
#Mann= 5 ,-1,0
       0      .1       0     150     .06       0   221.6    .045       0
   238.5     .06       0     270      .1       0
Bank Sta=221.6,238.5
XS Rating Curve= 0 ,0
Exp/Cntr(USF)=0,0
Exp/Cntr=0.3,0.1

Type RM Length L Ch R = 1 ,2032    ,310.1,312.6,316.7
XS GIS Cut Line= 2
2331389.61672129602431.3678982632331771.31345373602669.711357258
#Sta/Elev= 30
       0 3317.69     3.4 3314.97    29.3 3300.49    40.7 3293.45    50.2 3290.57
    59.6  3284.1    64.3 3281.55    81.6 3275.12   116.2 3265.14   130.3 3261.99
   163.4 3259.18   182.2 3256.53   191.6    3254   200.6 3253.14   210.5 3249.11
   219.9 3247.63     230 3249.04   238.8 3249.83   264.4  3249.7   270.3 3250.66
   282.8 3258.06   290.6 3261.73   342.6 3276.79   354.4 3282.33   366.1 3285.26
     385 3292.17   406.7 3298.08   422.7 3301.35   435.7 3306.99     450 3315.61
#Mann= 5 ,-1,0
       0      .1       0     190     .06       0   210.5    .045       0
     230     .06       0     300      .1       0
Bank Sta=210.5,230
XS Rating Curve= 0 ,0
Exp/Cntr(USF)=0,0
Exp/Cntr=0.3,0.1

Type RM Length L Ch R = 1 ,1719    ,254.6,259.4,263.7
XS GIS Cut Line= 2
2331269.27910836602648.3912662492331573.04522004602980.394503273
#Sta/Elev= 30
       0 3312.06     5.4 3308.86    17.3 3304.02    33.8 3299.11    63.5 3286.02
    79.1 3280.74      96  3272.4   104.1 3269.45   121.5 3259.47   128.7  3257.8
   141.3 3253.19   146.5 3251.69   152.4 3250.82   164.3 3250.36   176.1 3247.07
   189.5 3246.53   200.8 3243.25   223.5 3241.95   234.2 3241.28   239.6 3241.82
   251.8 3245.02   272.1 3248.53   288.6 3253.37   305.5 3259.73   320.9 3264.17
   370.7 3280.47   391.4 3288.71   410.3  3293.8   418.8 3297.41     450 3308.89
#Mann= 5 ,-1,0
       0      .1       0     120     .06       0   223.5    .045       0
   239.6     .06       0     270      .1       0
Bank Sta=223.5,239.6
XS Rating Curve= 0 ,0
Exp/Cntr(USF)=0,0
Exp/Cntr=0.3,0.1

Type RM Length L Ch R = 1 ,1460    ,247.9,255.9,258
XS GIS Cut Line= 3
2331185.50091799602741.8656015192331211.05551441602943.662765823
2331313.18576988603180.545842271
#Sta/Elev= 30
       0 3291.04    27.5 3282.98    47.7 3275.85    62.6 3271.57    75.9 3265.66
      84 3263.47      92 3259.72   100.1 3257.61   112.7 3252.05   130.6 3246.47
   148.6 3243.96   168.6  3242.9   180.7 3240.09   204.2 3242.05229.5723 3238.13
   238.9 3237.09247.67223238.055   254.1 3238.54   263.2 3240.62   274.8 3240.82
   296.5 3245.75   331.4 3249.73   357.6 3257.26   370.6 3262.41   375.9 3263.81
     385 3268.48   396.7 3272.91   421.5 3284.72   440.3 3296.49   461.4 3307.77
#Mann= 5 ,-1,0
       0      .1       0      30     .06       0     130      .1       0
229.5723    .045       0247.6722      .1       0
Bank Sta=229.5723,247.6722
XS Rating Curve= 0 ,0
Exp/Cntr(USF)=0,0
Exp/Cntr=0.3,0.1

Type RM Length L Ch R = 1 ,1204    ,210.6,210.9,211
XS GIS Cut Line= 2
 2331007.8689676602681.9834655742331043.32337747603130.584607816
#Sta/Elev= 30
       0  3292.7     7.2 3291.74    31.3 3284.51    71.4 3274.48   127.6 3257.64
   159.7 3249.14   167.7 3246.21   175.7 3242.33   179.8  3239.8   187.8 3233.75
  190.58 3232.56   199.8  3231.5   203.8 3231.59   207.9 3232.55   211.9 3233.44
   226.4 3234.06   235.9 3233.23   239.9 3233.41   251.5 3235.27     264  3236.3
   276.1 3236.14   300.1 3238.88   336.2 3238.85   360.4 3241.52   364.8 3242.51
   388.4 3250.99   400.4 3257.38   412.5 3261.77   424.5  3268.5     450 3281.17
#Mann= 5 ,-1,0
       0      .1       0     190     .06       0  190.58    .045       0
   207.9     .06       0     290      .1       0
Bank Sta=190.58,207.9
XS Rating Curve= 0 ,0
Exp/Cntr(USF)=0,0
Exp/Cntr=0.3,0.1

Type RM Length L Ch R = 1 ,993     ,302.5,289.3,270.5
XS GIS Cut Line= 2
2330818.51603247602694.3858857112330828.18469751603113.064104592
#Sta/Elev= 30
       0 3277.14    13.4 3271.16    47.4 3258.99    66.7 3253.73   106.8 3244.07
   126.8 3239.89   138.8 3238.09   150.8 3232.69   162.8 3229.58   166.8 3228.83
   186.8 3229.67   203.8  3228.7   218.9 3227.05   222.3 3225.89   226.9  3225.4
   234.9 3225.88   242.8 3229.36   250.9 3229.85   254.9 3231.17   262.9 3236.77
   266.9 3238.02   286.9 3240.31     292 3242.26   310.9  3251.8   318.9 3257.29
   326.9 3261.72   334.9 3267.24   350.9 3280.66   358.9 3285.45   418.8 3301.16
#Mann= 5 ,-1,0
       0      .1       0     180     .06       0   222.3    .045       0
   234.9     .06       0     280      .1       0
#XS Ineff= 2 , 0
           186.2 3233.43
Permanent Ineff=
       F       F
Bank Sta=222.3,234.9
XS Rating Curve= 0 ,0
Exp/Cntr(USF)=0,0
Exp/Cntr=0.3,0.1

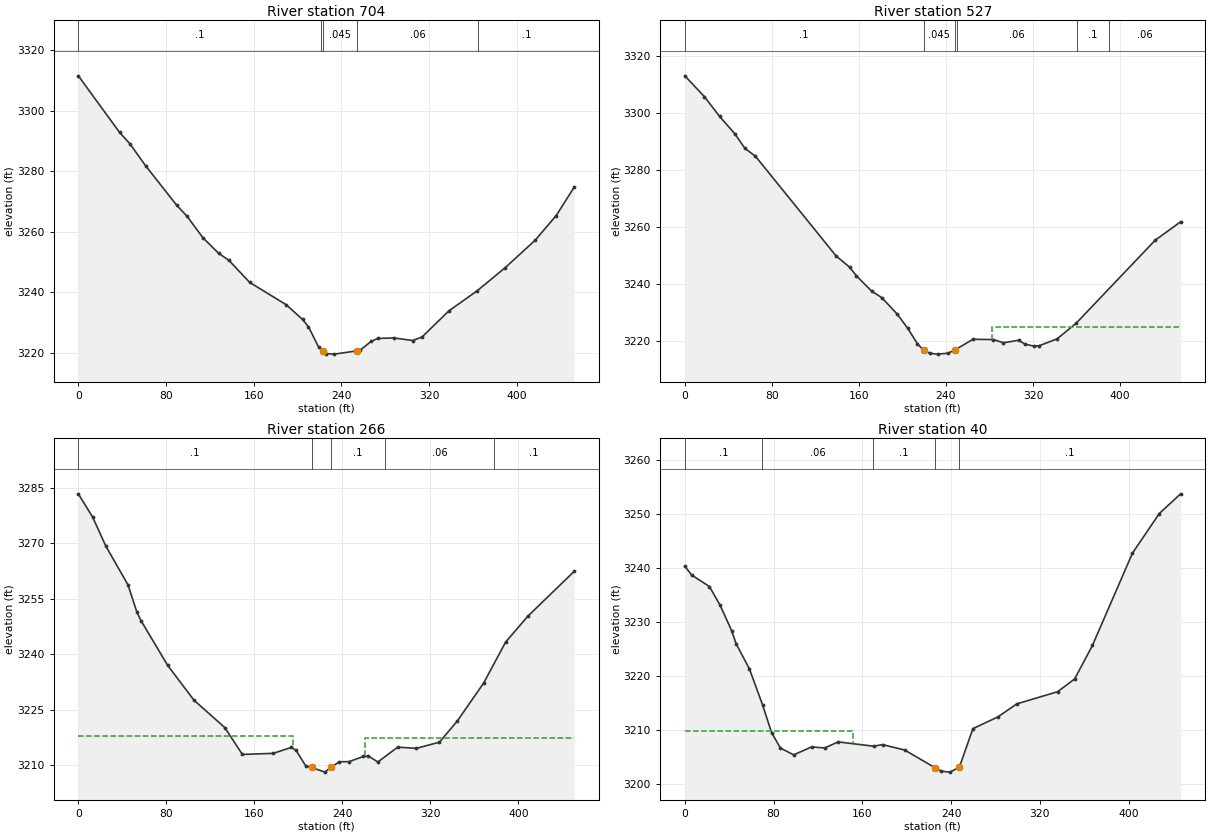
Type RM Length L Ch R = 1 ,704     ,181,176.5,173.6
XS GIS Cut Line= 4
2330435.26553776  602765.40224122330538.12051293602926.488940193
2330615.65555598602995.7755744122330714.71374581603117.950852503
#Sta/Elev= 30
       0 3311.48    37.7 3292.76    47.2 3288.96    61.4 3281.76    89.9 3268.66
    99.4 3265.01   113.6 3258.02   127.9 3252.89   137.4 3250.53   156.3 3243.25
   189.6 3235.88   204.6    3231     210 3228.57   219.2  3221.9   222.8 3220.57
   226.1 3219.72   233.5 3219.54     254 3220.61   256.8 3220.74   267.2 3223.76
   273.2 3224.72     288 3224.89     305 3224.04   313.5 3225.17   338.1 3233.83
   363.9 3240.46   389.6 3248.14   416.6 3257.09     436  3265.3   452.4 3274.68
#Mann= 5 ,-1,0
       0      .1       0  221.12     .06       0   222.8    .045       0
     254     .06       0  365.11      .1       0
Bank Sta=222.8,254
XS Rating Curve= 0 ,0
Exp/Cntr(USF)=0,0
Exp/Cntr=0.3,0.1

Type RM Length L Ch R = 1 ,527     ,275.4,261,245.7
XS GIS Cut Line= 2
2330252.68776935602967.6743376922330644.01570685603200.956729766
#Sta/Elev= 30
       0 3313.09      18  3305.8      32 3298.82      46 3292.73    55.3 3287.61
    64.9 3284.86   139.1 3249.82   151.4 3245.93   157.7 3242.87   171.7 3237.49
     181 3235.22     195 3229.51     205 3224.38   213.6 3219.09   219.5 3216.72
   225.4 3215.68   232.2 3215.38   241.6 3215.68   247.9 3216.78   264.8 3220.59
   283.5 3220.49   292.8 3219.37   306.8 3220.24   312.9 3218.81   320.7 3218.22
   325.4  3218.3   342.1 3220.73   359.6 3226.23   432.3  3255.4   455.6 3261.84
#Mann= 6 ,-1,0
       0      .1       0   219.5    .045       0   247.9      .1       0
     250     .06       0     360      .1       0     390     .06       0
#XS Ineff= 2 , 0
                          281.97         3225.02
Permanent Ineff=
       F       F
Bank Sta=219.5,247.9
XS Rating Curve= 0 ,0
Exp/Cntr(USF)=0,0
Exp/Cntr=0.3,0.1

Type RM Length L Ch R = 1 ,266     ,226.4,226.4,226.4
XS GIS Cut Line= 4
2330199.13283626603316.7236992442330387.99947212603322.412564303
2330505.95171847603270.4475886382330638.20017494603282.060835352
#Sta/Elev= 30
       0 3283.33      13 3277.05    25.1 3269.16    45.1 3258.77    53.1  3251.5
    57.1 3249.02    81.1 3237.05   105.1 3227.61   133.1 3220.23   149.1 3212.97
   177.1 3213.26   193.5 3214.85   197.9 3214.07   206.6 3209.89   211.9 3209.45
   224.1 3208.19   229.5 3209.48   237.2 3210.99     246 3211.02   259.1 3212.42
   263.5 3212.56   272.2 3210.92   290.2 3214.93   307.2 3214.61   328.1 3216.27
   344.2 3221.91   368.3 3232.22   388.3 3243.29   408.4 3250.26   450.6 3262.39
#Mann= 5 ,-1,0
       0      .1       0   211.9    .045       0   229.5      .1       0
  278.95     .06       0  377.84      .1       0
#XS Ineff= 2 , 0
          195.49  3217.9  260.56         3217.47
Permanent Ineff=
       F       F
Bank Sta=211.9,229.5
XS Rating Curve= 0 ,0
Exp/Cntr(USF)=0,0
Exp/Cntr=0.3,0.1

Type RM Length L Ch R = 1 ,40      ,,,
XS GIS Cut Line= 4
2330293.96761139603515.4253310572330468.00903783603517.075012824
2330567.81478474603498.1036725022330680.81798579603369.428494666
#Sta/Elev= 30
       0 3240.35     6.2 3238.71    22.2 3236.57    31.7 3233.14    42.2  3228.4
    46.2 3225.98    58.2 3221.31    70.2 3214.56    78.2 3209.47    86.2  3206.6
    98.2 3205.34   114.2 3206.81   126.2 3206.63   138.2 3207.75   170.1 3206.95
   178.3 3207.24   198.1 3206.25   225.4 3202.97   231.2  3202.3   239.1 3202.14
   247.5 3203.06   259.7 3210.21   282.2 3212.38   299.2  3214.8   336.1 3217.06
   351.4 3219.43   367.4 3225.64   403.5 3242.77   427.7 3250.12   446.9 3253.77
#Mann= 5 ,-1,0
       0      .1       0      70     .06       0     170      .1       0
   225.4    .045       0   247.5      .1       0
#XS Ineff= 2 , 0
          151.27 3209.83
Permanent Ineff=
       F       F
Bank Sta=225.4,247.5
XS Rating Curve= 0 ,0
Exp/Cntr(USF)=0,0
Exp/Cntr=0.3,0.1
LCMann Table=0

Chan Stop Cuts=-1
Use User Specified Reach Order=0
Composite Channel Slope=5